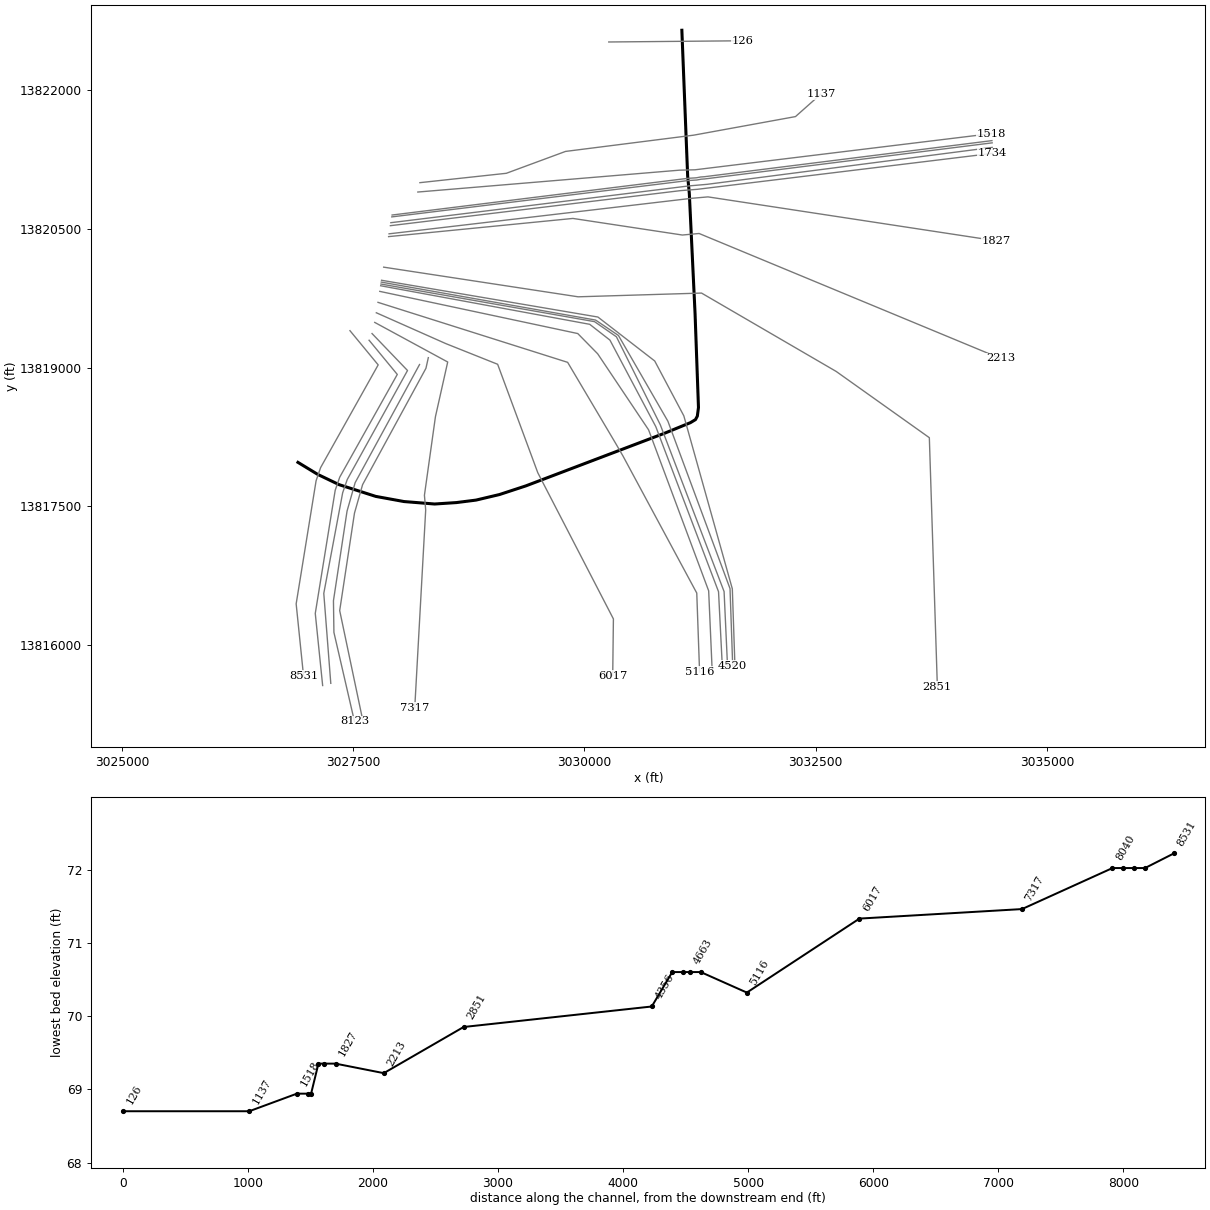
--- D132-00-00_Updated.prj (project) ---

Proj Title=D132-00-00
Current Plan=p07
Default Exp/Contr=.3,.1
English Units
Geom File=g02
Geom File=g03
Flow File=f01
Flow File=f05
Plan File=p06
Plan File=p07
Y Axis Title=Elevation
X Axis Title(PF)=Main Channel Distance
X Axis Title(XS)=Station
BEGIN DESCRIPTION:
Brays Bayou Watershed
Tributary 29.16
HCFCD Unit D132-00-00
Flood Hazard & Floodway Model
10, 2, 1, 0.2% Event
Filename D1320000.prj
Prepared by: Dodson & Associates, Inc.   Date: September 2003
Reviewed by:____________________	 Date:_________
STATUS (Final RAS, SVSQ)
END DESCRIPTION:
DSS Export Rating Curves= 0
DSS Export Rating Curve Sorted= 0
DSS Export Volume Flow Curves= 0
DXF OffsetX= 0
DXF OffsetY= 0
DXF ScaleX= 1
DXF ScaleY= 10

--- D132-00-00_Updated.p07 (plan) ---

Plan Title=FEMA Effective FW
Version=Version 3.0.1  Mar 2001
Short Identifier=Eff+LOMR FW
Geom File=g02
Flow File=f05
Subcritical Flow
K Sum by GR= 0
Std Step Tol= 0.01
Critical Tol= 0.01
Num of Std Step Trials= 20
Max Error Tol= 0.3
Flow Tol Ratio= 0.001
Split Flow NTrial= 30
Split Flow Tol= 0.02
Split Flow Ratio= 0.02
Log Output Level= 0
Friction Slope Method= 0
Unsteady Friction Slope Method= 2
Calc Critical at every XS
Secant Critical Depth
Global Vel Dist= 0 , 0 , 0
Global Log Level= 0
CheckData=True
Encroach Param=-1 ,0,0, 2
Encroach River=D132-00-00
Encroach Reach=D132-00-00_0001
Encroach Node=8531
       1 1784.83 1884.41
Encroach Node=8300
       1 1781.01  1878.5
Encroach Node=8215
       1 1936.01 2037.41
Encroach Node=8169
       1 1481.01 2037.41
Encroach Node=8123
       1 1481.01  1578.5
Encroach Node=8040
       1 1588.01  1685.5
Encroach Node=7317
       1 2388.47 2490.96
Encroach Node=6017
       1 2708.59 2803.23
Encroach Node=5116
       1 3198.42 3292.95
Encroach Node=4748
       1  3485.6 3627.58
Encroach Node=4663
       1  3646.6 3788.58
Encroach Node=4636
       1  3646.6 3836.58
Encroach Node=4609
       1  3694.6 3836.58
Encroach Node=4520
       1  3733.6 3875.58
Encroach Node=4356
       1 3820.43 3955.92
Encroach Node=2851
       1 3324.61 3431.51
Encroach Node=2213
       1 3244.99 3355.32
Encroach Node=1827
       1 3215.27 3332.88
Encroach Node=1734
       1 3192.27  3302.5
Encroach Node=1712
       1 3179.27  3289.5
Encroach Node=1690
       1 3179.27  3289.5
Encroach Node=1632
       1  3162.3 3276.98
Encroach Node=1620
       1 3164.02 3276.98
Encroach Node=1608
       1 3164.02 3276.98
Encroach Node=1518
       1 2867.02 2983.08
Encroach Node=1137
       1  2877.8 3016.67
Encroach Node=126
       1  718.35  868.36
BEGIN DESCRIPTION:
FEMA Effective 2007 + LOMR 10-06-0053P
END DESCRIPTION:
Computation Interval=1HOUR
Output Interval=1HOUR
Run HTab= 0
Run UNet= 0
Run PostProcess= 0
UNET Theta= 1
UNET ZTol= 0.02
UNET ZSATol= 0.1
UNET MxIter= 20
UNET MaxInSteps= 20
UNET DtIC= 0
UNET DtMin= 0
UNET MaxCRTS= 20
UNET WFStab= 2
UNET SFStab= 1
UNET WFX= 1
UNET SFX= 1
UNET Convert EG Bridges=-1
UNET Use Existing IB Tables=-1
Instantaneous Interval=1HOUR
Write IC File= 0
Write Velocity= 0
Write Detailed= 0

--- D132-00-00_Updated.p06 (plan) ---

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Plan Title=FEMA Effective MP
Short Identifier=Eff+LOMR MP
Geom File=g02
Flow File=f01

--- D132-00-00_Updated.f05 (steady flow) ---

Flow Title=Floodway
Version=Version 3.0.1  Mar 2001
Number of Profiles= 2
Profile Names=1PCT_100yr,Floodway
River Rch & RM=D132-00-00,D132-00-00_0001 ,8531
    1392    1392
River Rch & RM=D132-00-00,D132-00-00_0001 ,8040
    1502    1502
River Rch & RM=D132-00-00,D132-00-00_0001 ,7317
    1721    1721
River Rch & RM=D132-00-00,D132-00-00_0001 ,6017
    1891    1891
River Rch & RM=D132-00-00,D132-00-00_0001 ,5116
    2047    2047
River Rch & RM=D132-00-00,D132-00-00_0001 ,4356
    2389    2389
River Rch & RM=D132-00-00,D132-00-00_0001 ,2851
    2740    2740
River Rch & RM=D132-00-00,D132-00-00_0001 ,1518
    3162    3162
Boundary for River Rch & Prof#=D132-00-00,D132-00-00_0001 , 1
Up Type= 0
Dn Type= 1
Dn Known WS=82.31
Boundary for River Rch & Prof#=D132-00-00,D132-00-00_0001 , 2
Up Type= 0
Dn Type= 1
Dn Known WS=83.31
DSS Import GetInterval= 0
DSS Import GetPeak= 0
DSS Import FillOption= 0

--- D132-00-00_Updated.f01 (steady flow) ---

Flow Title=FEMA Effective June 2007
Version=Version 3.0.1  Mar 2001
Number of Profiles= 4
Profile Names=10PCT_10yr,2PCT_50yr,1PCT_100yr,0.2PCT_500yr
River Rch & RM=D132-00-00,D132-00-00_0001 ,8531
     791    1188    1392    1988
River Rch & RM=D132-00-00,D132-00-00_0001 ,8040
     854    1282    1502    2142
River Rch & RM=D132-00-00,D132-00-00_0001 ,7317
     980    1470    1721    2449
River Rch & RM=D132-00-00,D132-00-00_0001 ,6017
    1078    1616    1891    2688
River Rch & RM=D132-00-00,D132-00-00_0001 ,5116
    1169    1750    2047    2907
River Rch & RM=D132-00-00,D132-00-00_0001 ,4356
    1368    2044    2389    3386
River Rch & RM=D132-00-00,D132-00-00_0001 ,2851
    1573    2347    2740    3877
River Rch & RM=D132-00-00,D132-00-00_0001 ,1518
    1819    2710    3162    4465
Boundary for River Rch & Prof#=D132-00-00,D132-00-00_0001 , 1
Up Type= 0
Dn Type= 3
Dn Slope=.0006
Boundary for River Rch & Prof#=D132-00-00,D132-00-00_0001 , 2
Up Type= 0
Dn Type= 3
Dn Slope=.0006
Boundary for River Rch & Prof#=D132-00-00,D132-00-00_0001 , 3
Up Type= 0
Dn Type= 3
Dn Slope=.0006
Boundary for River Rch & Prof#=D132-00-00,D132-00-00_0001 , 4
Up Type= 0
Dn Type= 3
Dn Slope=.0006
DSS Import GetInterval= 0
DSS Import GetPeak= 0
DSS Import FillOption= 0

--- D132-00-00_Updated.g02 (geometry) ---

Geom Title=D132-00-00
Version=Version 3.0.1  Mar 2001

River Reach=D132-00-00      ,D132-00-00_0001
Reach XY= 19
       3026904.3       13817975.       3027119.4      13817844.2
        3027349.       13817734.       3027745.1      13817607.2
       3028050.1      13817551.5       3028381.7      13817524.8
       3028617.6      13817540.4       3028829.1      13817567.1
       3029082.8      13817627.2       3029367.7      13817720.7
       3030872.7      13818291.9       3031147.3      13818404.4
       3031201.8      13818437.4       3031221.8      13818475.2
        3031234.      13818568.4       3031197.3      13819579.2
        3031135.      13820881.3       3031117.2      13821068.3
       3031054.4      13822646.2

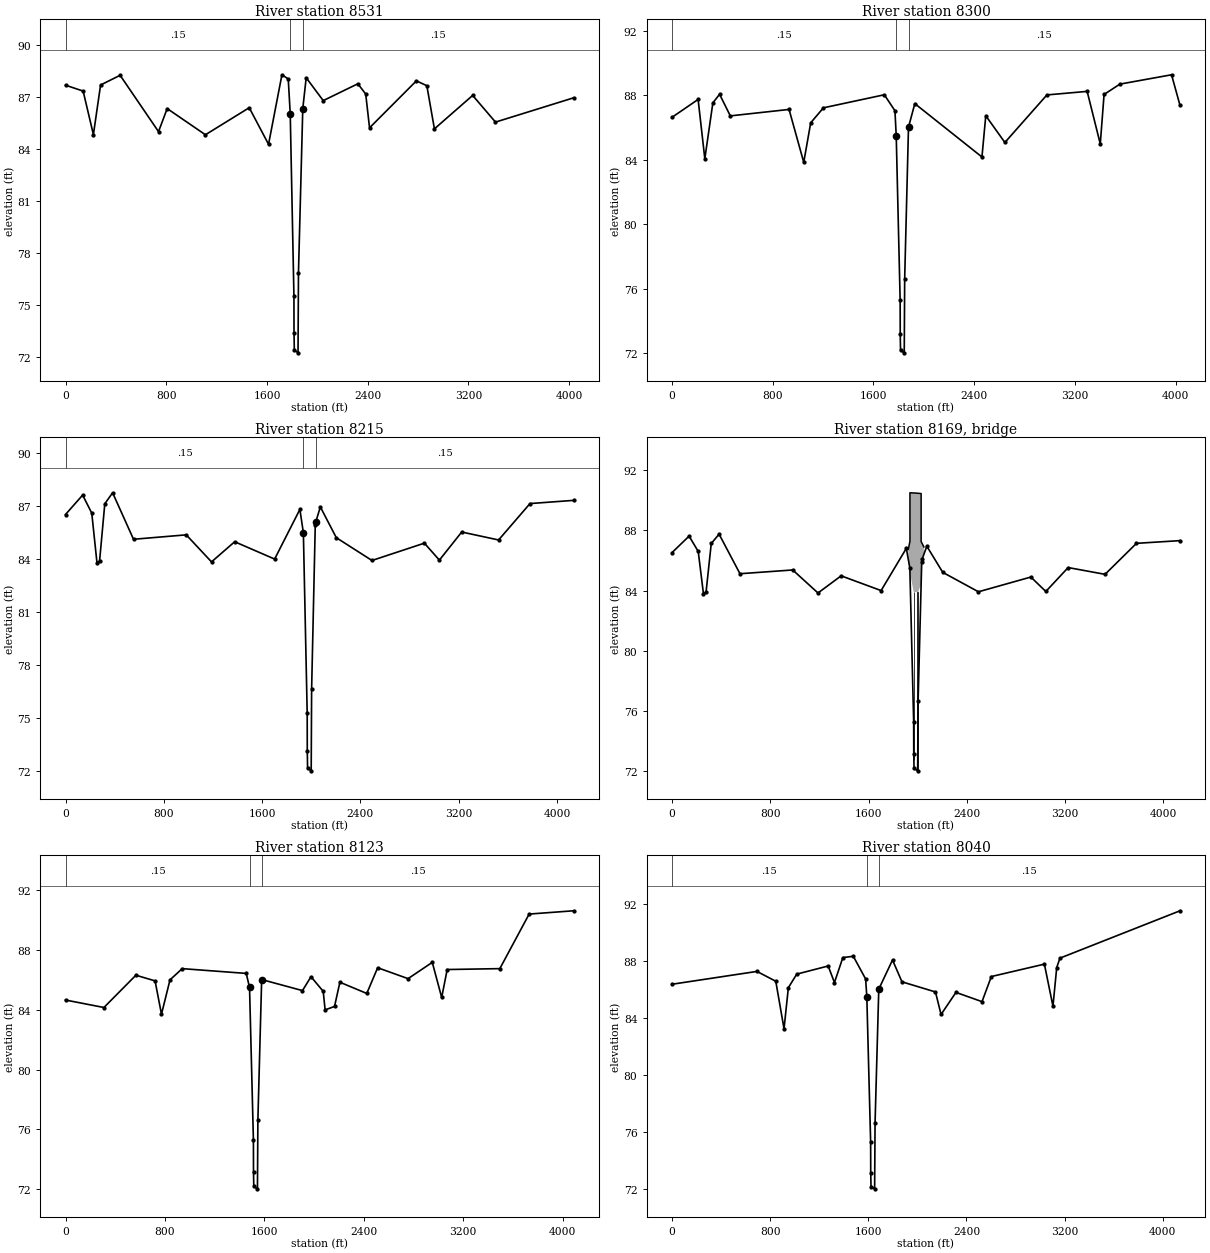
Type RM Length L Ch R = 1 ,8531    ,231.87,231.03,227.33
BEGIN DESCRIPTION:
Added Cross Section to Meet LODS
END DESCRIPTION:
XS GIS Cut Line= 6
      3027466.56    13819398.623     3027771.483    13819028.847
     3027149.468    13817918.789     3027100.312    13817776.395
     3026884.868    13816445.409     3026964.674    13815665.767
#Sta/Elev= 30
       0   87.66  139.98   87.32  221.53   84.81  278.51   87.67  433.73   88.23
  738.74   84.98  807.52   86.31 1111.19    84.8 1459.13   86.36 1612.56   84.25
 1718.82   88.26 1768.96   88.02 1784.83   86.01  1814.2   75.47 1814.86   73.36
 1817.27   72.38  1846.7   72.22 1850.15   76.83 1884.41   86.31 1911.51   88.09
  2046.8   86.77 2321.73   87.74 2384.24   87.15 2414.58    85.2 2786.76   87.91
 2869.73   87.63 2929.84   85.14  3233.6   87.07  3414.9   85.53 4034.85   86.93
#Mann= 3 , 0 , 0
       0     .15       0 1784.83     .04       0 1884.41     .15       0
#XS Ineff= 2 , 0
       0    1750            1915       0
Permanent Ineff=
       F       F
Bank Sta=1784.83,1884.41
XS Rating Curve= 0
Exp/Cntr=.3,.1

Type RM Length L Ch R = 1 ,8300    ,83.08,85.12,85.28
XS GIS Cut Line= 6
     3027673.125    13819295.368     3027978.045    13818925.592
      3027356.03    13817815.534     3027306.874     13817673.14
      3027091.43    13816342.154     3027171.236    13815562.512
#Sta/Elev= 30
       0   86.63   207.6   87.74  260.88   84.06  324.81   87.53  378.09   88.06
  463.33   86.72  929.88   87.12 1046.48   83.84 1101.82   86.29 1202.92   87.22
 1686.43   88.03 1770.81   87.04 1781.01   85.49  1812.2   75.27 1812.86   73.16
 1815.27   72.18  1844.7   72.02 1848.15   76.63  1878.5   86.02  1928.7   87.48
 2461.86   84.17 2492.21   86.73 2643.92   85.07  2977.7   88.02  3297.4   88.24
 3401.58   84.98 3431.73   88.05 3557.28   88.69 3967.63   89.27 4034.86   87.37
#Mann= 3 , 0 , 0
       0     .15       0 1781.01     .04       0  1878.5     .15       0
#XS Ineff= 2 , 0
       0    1739            1900       0
Permanent Ineff=
       T       T
Bank Sta=1781.01,1878.5
XS Rating Curve= 0
Exp/Cntr=.5,.3

Type RM Length L Ch R = 1 ,8215    ,91.88,92,91.78
XS GIS Cut Line= 6
     3027705.189    13819367.342     3028088.621    13818968.105
      3027436.82    13817789.074     3027387.664     13817646.68
     3027183.462     13816558.46     3027259.185    13815586.272
#Sta/Elev= 30
       0   86.52  139.44   87.62   213.7    86.6  256.13   83.79  277.35   83.89
  319.79   87.13  383.44   87.75  553.54   85.12  982.72   85.37  1188.4   83.84
 1376.93   84.98 1702.09      84  1907.7   86.81 1936.01   85.49  1967.2   75.27
 1967.86   73.16 1970.27   72.18  1999.7   72.02 2003.15   76.63 2032.77   85.92
 2037.41   86.11 2074.12   86.95 2204.09   85.21  2494.3   83.92 2921.01    84.9
 3042.93   83.94 3224.79   85.53 3524.99   85.08  3780.7   87.14 4135.05   87.32
#Mann= 3 , 0 , 0
       0     .15       0 1936.01     .04       0 2037.41     .15       0
#XS Ineff= 2 , 0
       0    1885            2055       0
Permanent Ineff=
       T       T
Bank Sta=1936.01,2037.41
XS Rating Curve= 0
Exp/Cntr=.5,.3

Type RM Length L Ch R = 3 ,8169    ,,,
BEGIN DESCRIPTION:
Addicks-Clodine Bridge
END DESCRIPTION:
Bridge Culvert--1,0,-1,-1, 0
Deck Dist Width WeirC Skew NumUp NumDn MinLoCord MaxHiCord MaxSubmerge Is_Ogee
5,80,2.6,0, 7, 7, , , .95, 0, 0,0,,
 1923.58 1936.87 1936.87 1983.87 2027.97 2027.97 2050.54
   86.74   87.28    90.5   90.48   90.45   87.26    86.9
       0       0   83.94    83.9   83.88       0       0
  1454.5 1482.87 1482.87 1529.87 1573.97 1573.97 1605.12
   86.23   87.28    90.5   90.48   90.45   87.26   86.54
       0       0   83.94    83.9   83.88       0       0
Pier Skew, UpSta & Num, DnSta & Num=  ,1968.87, 2 ,1514.87, 2 , 0 , 0 , 0 ,,
    1.25    1.25
       0     100
    1.25    1.25
       0     100
Pier Skew, UpSta & Num, DnSta & Num=  ,1998.87, 2 ,1544.87, 2 , 0 , 0 , 0 ,,
    1.25    1.25
       0     100
    1.25    1.25
       0     100
BR Coef=-1 , 1 , 1 ,1.25, 0 ,,,.8,-1,2,0,
WSPro=,,,, 1 ,,,, 0 ,,,, 0 ,,,,-1 ,-1 ,-1 , 0 , 0 , 0 , 0 , 0
BC Design=,, 0 ,, 0 ,,,,,,
BC HTab HWMax=88.09

Type RM Length L Ch R = 1 ,8123    ,82.08,83.04,83.79
XS GIS Cut Line= 6
     3028218.652    13819032.687     3027522.669    13817755.895
     3027434.945    13817448.171     3027287.974    13816479.592
     3027292.996    13816137.085     3027515.201    13815174.269
#Sta/Elev= 30
       0   84.65  309.17   84.15  566.45   86.31  720.82   85.93  772.28    83.7
  840.89      86  939.36   86.75 1454.49   86.43 1481.01   85.49  1512.2   75.27
 1512.86   73.16 1515.27   72.18  1544.7   72.02 1548.15   76.63  1578.5   86.02
 1907.06   85.28 1975.48   86.21 2073.95   85.23 2089.12   83.99 2164.98   84.22
    2208   85.84 2424.44   85.09 2512.06   86.81 2756.66   86.08 2951.68   87.17
 3027.21   84.82 3071.57   86.69 3495.15   86.75 3731.06    90.4 4088.41   90.62
#Mann= 3 , 0 , 0
       0     .15       0 1481.01     .04       0  1578.5     .15       0
#XS Ineff= 2 , 0
       0    1431            1610       0
Permanent Ineff=
       T       T
Bank Sta=1481.01,1578.5
XS Rating Curve= 0
Exp/Cntr=.5,.3

Type RM Length L Ch R = 1 ,8040    ,660.54,723.15,762.55
XS GIS Cut Line= 6
     3028313.518    13819107.079     3028287.961    13818992.184
     3027603.154    13817734.614      3027515.43     13817426.89
     3027355.475    13816372.746     3027603.326     13815194.16
#Sta/Elev= 30
       0   86.36  692.36   87.26  846.08   86.57  913.25   83.24  948.56   86.12
 1016.88   87.07 1273.08   87.64 1324.32   86.48 1392.64   88.23 1478.03   88.32
 1578.32   86.73 1588.01   85.49  1619.2   75.27 1619.86   73.16 1622.27   72.18
  1651.7   72.02 1655.15   76.63  1685.5   86.02 1797.54   88.06 1874.49   86.53
 2147.58   85.82 2193.09   84.24 2314.47   85.79 2526.87   85.14 2602.73    86.9
 3035.27   87.77 3105.12   84.82 3135.78   87.53 3161.92   88.19 4140.62   91.51
#Mann= 3 , 0 , 0
       0     .15       0 1588.01     .04       0  1685.5     .15       0
#XS Ineff= 2 , 0
       0    1540            1730       0
Permanent Ineff=
       T       T
Bank Sta=1588.01,1685.5
XS Rating Curve= 0
Exp/Cntr=.3,.1

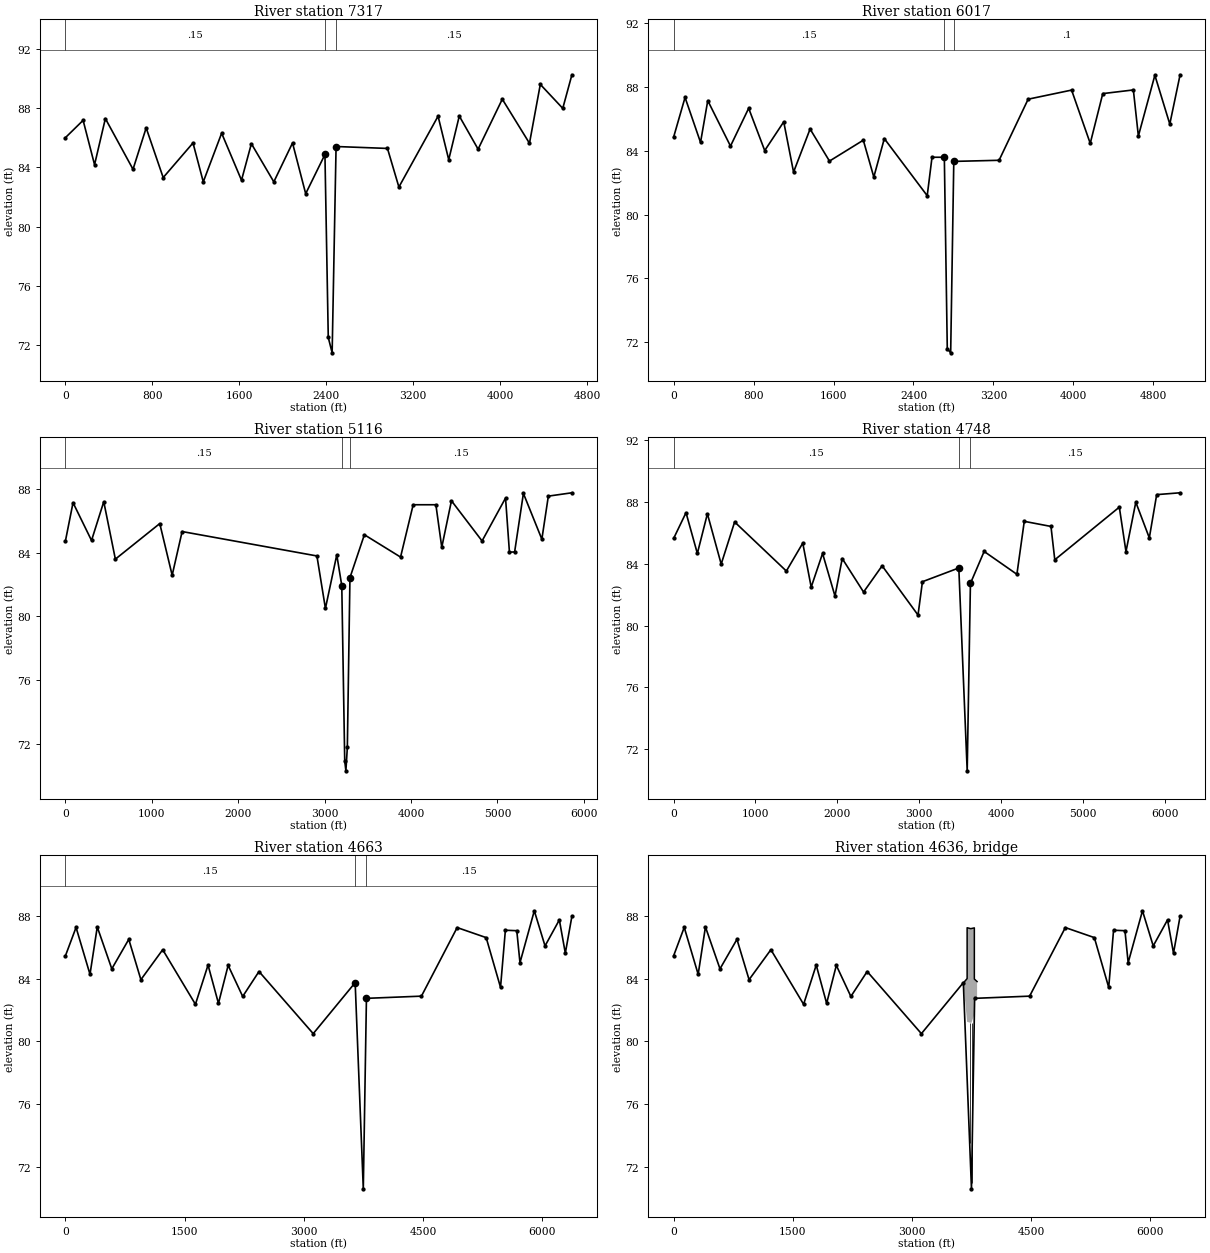
Type RM Length L Ch R = 1 ,7317    ,1223.48,1300.11,1383.91
XS GIS Cut Line= 6
     3027734.421    13819487.906     3028523.086    13819059.886
     3028390.559    13818469.119     3028271.462    13817619.461
     3028285.096    13817459.822       3028166.9    13815322.506
#Sta/Elev= 30
       0   86.01  162.79   87.18  268.08   84.18  367.59    87.3  622.08   83.87
  743.06   86.67   899.7   83.31 1174.11   85.65 1268.72   83.02 1437.82   86.31
 1620.53   83.13 1711.41    85.6 1917.99   83.02 2090.08   85.65 2211.25   82.22
 2388.47   84.87 2419.13    72.5 2454.76   71.46 2490.96   85.41 2963.96   85.28
 3069.12   82.67 3429.67   87.46 3527.82   84.52 3624.97   87.47 3798.16   85.23
 4020.79   88.61 4270.95   85.63 4370.64   89.61 4577.37   87.99 4661.54   90.26
#Mann= 3 , 0 , 0
       0     .15       0 2388.47     .04       0 2490.96     .15       0
#XS Ineff= 2 , 0
       0    2362            2528       0
Permanent Ineff=
       T       T
Bank Sta=2388.47,2490.96
XS Rating Curve= 0
Exp/Cntr=.3,.1

Type RM Length L Ch R = 1 ,6017    ,867.03,900.41,911.62
XS GIS Cut Line= 6
     3027751.287    13819592.301     3028503.556    13819258.517
     3029063.008    13819035.336     3029497.123    13817862.521
     3030314.371    13816282.652     3030306.892     13815670.11
#Sta/Elev= 30
       0   84.85  114.44   87.34  269.36   84.52  341.77   87.14  569.11   84.29
  750.98   86.66  911.47   84.01 1101.78   85.81 1200.08   82.66  1365.5   85.36
 1559.43   83.35 1897.97   84.66 2003.03   82.35 2108.09   84.76  2537.3   81.18
 2585.29   83.59 2708.59   83.59 2738.06   71.59 2771.97   71.33 2803.23   83.33
 3256.29    83.4 3547.17   87.23 3981.75    87.8 4168.34   84.46 4293.75   87.58
 4599.81   87.81 4649.91   84.92 4814.92   88.73 4964.29   85.67 5067.33   88.76
#Mann= 3 , 0 , 0
       0     .15       0 2708.59     .04       0 2803.23      .1       0
#XS Ineff= 2 , 0
       0    2677            3236       0
Permanent Ineff=
       T       T
Bank Sta=2708.59,2803.23
XS Rating Curve= 0
Exp/Cntr=.3,.1

Type RM Length L Ch R = 1 ,5116    ,401.12,368.54,343.94
XS GIS Cut Line= 6
     3027769.464    13819704.816     3029819.705    13819056.305
     3030336.918    13818183.405     3030417.304    13818044.801
     3031215.512    13816562.179      3031245.97    13815709.901
#Sta/Elev= 30
       0   84.73   87.93   87.13   302.1   84.76  443.69   87.19  577.96   83.59
 1091.89   85.82 1235.32   82.58  1350.6   85.32 2910.61   83.79 3009.15    80.5
 3140.52   83.86 3198.42   81.93 3232.45   70.95 3245.93   70.32 3262.83    71.8
 3292.95   82.43 3459.94   85.12 3878.65   83.72 4024.71      87 4287.51      87
 4355.65   84.33 4467.66   87.25 4822.03   84.73 5093.78   87.42 5138.81   84.03
 5198.85   84.04  5300.5   87.71 5514.05   84.84  5589.1   87.54 5861.88   87.75
#Mann= 3 , 0 , 0
       0     .15       0 3198.42     .04       0 3292.95     .15       0
#XS Ineff= 2 , 0
       0    3175            3379       0
Permanent Ineff=
       T       T
Bank Sta=3198.42,3292.95
XS Rating Curve= 0
Exp/Cntr=.3,.1

Type RM Length L Ch R = 1 ,4748    ,76.14,85.01,86.28
XS GIS Cut Line= 6
      3027788.64    13819823.512     3029929.209    13819367.521
     3030144.413     13819148.59     3030694.924     13818326.26
     3031344.136     13816586.31     3031381.261    13815741.734
#Sta/Elev= 30
       0   85.65  151.61   87.32  290.23   84.68  412.92   87.25  581.48   83.99
  745.84   86.72 1378.01   83.54  1578.5   85.35 1681.45    82.5 1820.52   84.68
 1972.24   81.92 2060.74   84.35 2321.68   82.18 2548.48   83.88 2986.98   80.69
 3041.08   82.85  3485.6   83.74 3588.03    70.6 3627.58   82.74 3795.19   84.81
 4195.56   83.33  4285.6   86.76 4611.95   86.43 4658.58   84.27 5447.32   87.68
 5528.55    84.8 5648.67      88 5813.83   85.69 5903.91   88.49 6189.96   88.61
#Mann= 3 , 0 , 0
       0     .15       0  3485.6     .04       0 3627.58     .15       0
#XS Ineff= 2 , 0
       0    3451            3655       0
Permanent Ineff=
       T       T
Bank Sta=3485.6,3627.58
XS Rating Curve= 0
Exp/Cntr=.5,.3

Type RM Length L Ch R = 1 ,4663    ,96.74,53.62,54.6
XS GIS Cut Line= 6
     3027798.457    13819884.276     3030058.267    13819467.443
     3030277.097     13819296.45     3030772.721     13818361.03
     3031450.873    13816576.586     3031492.677    13815749.693
#Sta/Elev= 30
       0   85.45  133.77   87.26  309.17   84.27  400.69   87.29  583.73   84.62
  797.27    86.5   949.8   83.93 1224.35   85.84 1636.19   82.36 1794.99   84.86
    1926   82.42 2048.02   84.84 2231.06   82.86 2436.27   84.45 3118.71   80.49
  3646.6   83.74 3749.03    70.6 3788.58   82.74 4480.78   82.88 4930.33   87.25
 5295.53   86.61  5476.2   83.44 5537.29   87.08 5680.87   87.05 5721.06   85.01
 5901.29   88.32 6036.47   86.08  6216.7   87.74 6291.79   85.62  6374.7   87.97
#Mann= 3 , 0 , 0
       0     .15       0  3646.6     .04       0 3788.58     .15       0
#XS Ineff= 2 , 0
       0    3642            3860       0
Permanent Ineff=
       T       T
Bank Sta=3646.6,3788.58
XS Rating Curve= 0
Exp/Cntr=.5,.3

Type RM Length L Ch R = 3 ,4636    ,,,
BEGIN DESCRIPTION:
Winkleman Bridge
END DESCRIPTION:
Bridge Culvert--1,0,-1,-1, 0
Deck Dist Width WeirC Skew NumUp NumDn MinLoCord MaxHiCord MaxSubmerge Is_Ogee
5,48,2.6,0, 7, 7, , , .95, 0, 0,0,,
 3646.68 3694.21 3694.21 3740.21 3785.21 3785.21 3819.79
   83.72      84   87.24   87.18   87.23   83.97   83.81
   81.24   81.24   81.24   81.18   81.23       0       0
 3694.58 3743.21 3743.21 3789.21 3834.21 3834.21 3868.53
   83.73      84   87.24   87.18   87.23   83.97      84
   81.24   81.24   81.24   81.18   81.23       0       0
Pier Skew, UpSta & Num, DnSta & Num=  ,3726.21, 2 ,3775.21, 2 , 0 , 0 , 0 ,,
    1.25    1.25
       0     100
    1.25    1.25
       0     100
Pier Skew, UpSta & Num, DnSta & Num=  ,3750.21, 2 ,3799.21, 2 , 0 , 0 , 0 ,,
    1.25    1.25
       0     100
    1.25    1.25
       0     100
BR Coef=-1 , 1 , 1 ,1.25, 0 ,,,.8,-1,2,0,
WSPro=,,,, 1 ,,,, 0 ,,,, 0 ,,,,-1 ,-1 ,-1 , 0 , 0 , 0 , 0 , 0
BC Design=,, 0 ,, 0 ,,,,,,
BC HTab HWMax=88.32

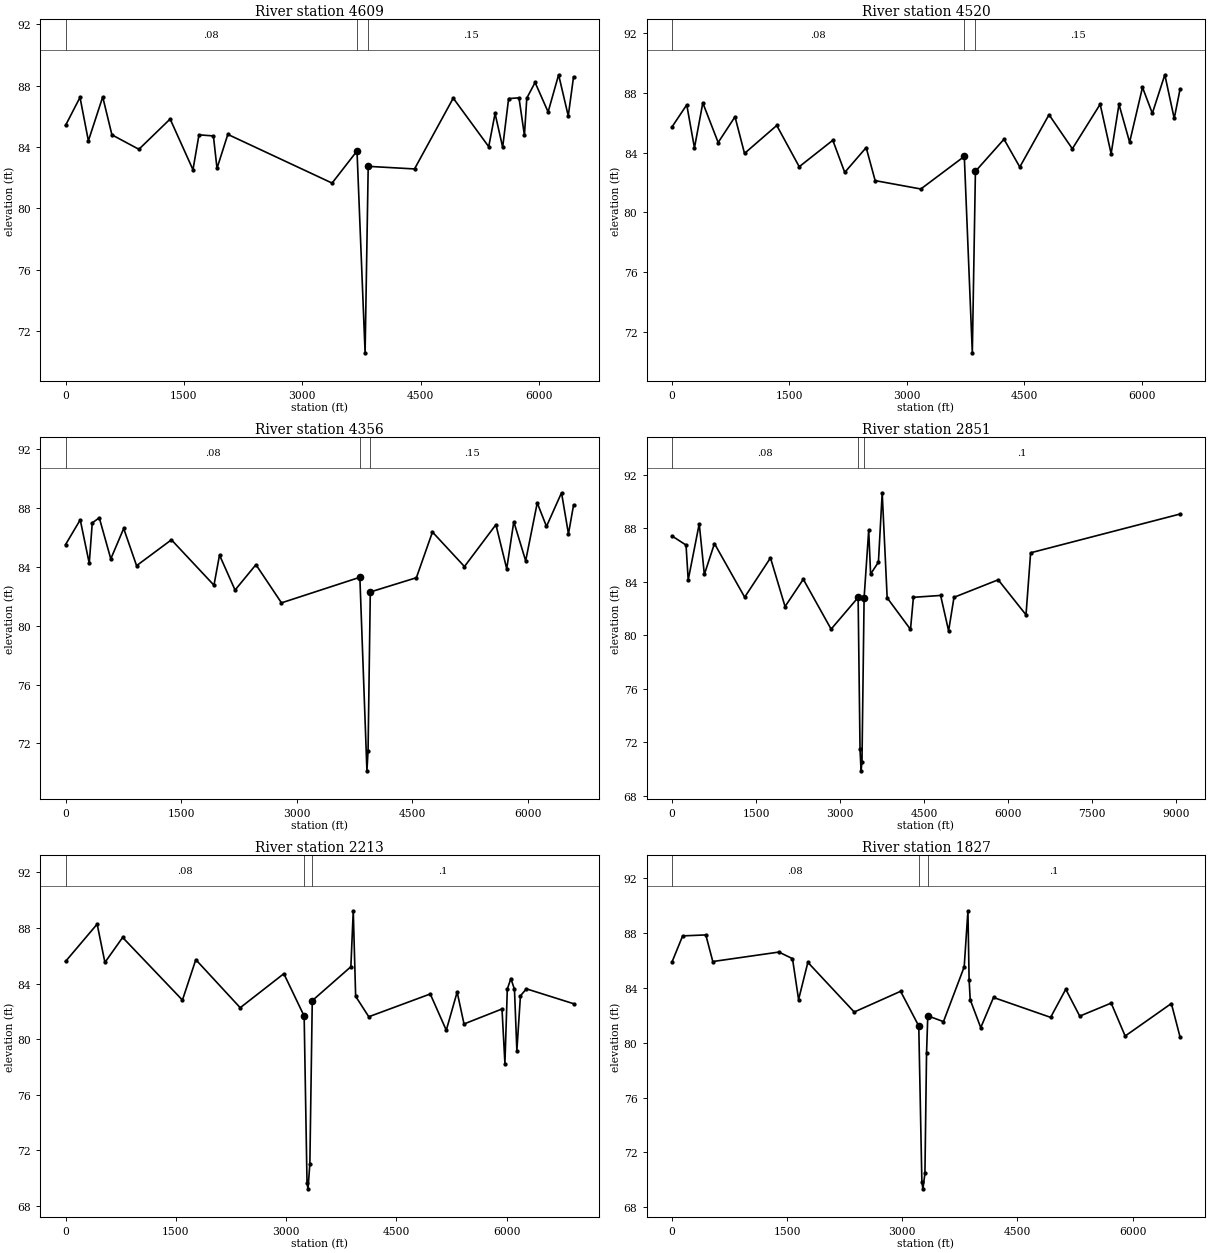
Type RM Length L Ch R = 1 ,4609    ,74.36,89.42,87.04
XS GIS Cut Line= 6
     3027801.445    13819902.773     3030110.254    13819496.294
     3030346.978     13819332.56     3030821.093    13818381.775
     3031510.919     13816578.24     3031548.385    13815765.609
#Sta/Elev= 30
       0    85.4  183.84   87.23  289.94    84.4  471.69   87.26  588.24   84.79
  930.14   83.85 1326.14   85.82 1615.52   82.52 1691.68   84.79 1874.45   84.72
 1920.14   82.61 2057.22   84.82  3378.7   81.65  3694.6   83.74 3797.03    70.6
 3836.58   82.74 4423.44   82.57 4914.19   87.18 5363.98   84.02  5444.3   86.18
 5540.68   83.98    5616   87.15  5747.4    87.2  5816.5   84.76 5846.53   87.18
 5951.64    88.2 6116.82   86.28 6249.79    88.7 6372.09   86.02 6439.05   88.57
#Mann= 3 , 0 , 0
       0     .08       0  3694.6     .04       0 3836.58     .15       0
#XS Ineff= 2 , 0
       0    3656            3917       0
Permanent Ineff=
       T       T
Bank Sta=3694.6,3836.58
XS Rating Curve= 0
Exp/Cntr=.5,.3

Type RM Length L Ch R = 1 ,4520    ,254.72,163.81,128.25
XS GIS Cut Line= 6
     3027804.815    13819923.632      3030121.61    13819513.419
      3030368.94     13819346.66     3030903.602     13818419.54
     3031575.037     13816610.22     3031604.093    13815773.567
#Sta/Elev= 30
       0   85.71  188.79   87.19  287.08   84.31  393.72   87.32  589.99   84.67
  805.01   86.39  926.48   83.94 1338.18   85.81 1625.34   83.05 2054.15   84.82
 2206.48   82.67  2480.2   84.33 2595.12   82.12 3178.34   81.56  3733.6   83.74
 3836.03    70.6 3875.58   82.74 4240.69   84.89 4442.22   83.03 4815.52   86.53
 5113.32   84.25  5468.8   87.23 5608.79   83.92 5709.17   87.22    5845   84.69
 6009.36   88.36 6135.11   86.62 6294.53    89.2  6414.6   86.28 6488.58   88.22
#Mann= 3 , 0 , 0
       0     .08       0  3733.6     .04       0 3875.58     .15       0
#XS Ineff= 2 , 0
       0    3616            3940       0
Permanent Ineff=
       T       T
Bank Sta=3733.6,3875.58
XS Rating Curve= 0
Exp/Cntr=.3,.1

Type RM Length L Ch R = 1 ,4356    ,738.93,1504.49,1647.82
XS GIS Cut Line= 6
     3027808.032    13819943.547      3030146.83    13819546.146
     3030761.017     13819071.02     3031075.755    13818477.736
     3031599.936    13816607.647     3031627.968    13815781.526
#Sta/Elev= 30
       0   85.52  191.19   87.21  308.24   84.25  347.25      87  438.29   87.35
  587.77   84.55  755.14   86.62   922.5   84.09 1374.66   85.85 1926.69   82.76
 1998.91   84.81 2200.56   82.43 2471.63   84.16 2803.03   81.56 3820.43    83.3
 3912.01   70.13 3926.84    71.5 3955.92    82.3 4553.88   83.27 4762.65   86.38
 5177.94   84.03 5586.05   86.88 5726.51   83.88  5818.2   87.08 5972.46   84.42
 6122.55   88.36 6242.61   86.76 6437.73   89.05 6527.78   86.25 6593.79   88.21
#Mann= 3 , 0 , 0
       0     .08       0 3820.43     .04       0 3955.92     .15       0
#XS Ineff= 2 , 0
       0    3574            4041       0
Permanent Ineff=
       T       T
Bank Sta=3820.43,3955.92
XS Rating Curve= 0
Exp/Cntr=.3,.1

Type RM Length L Ch R = 1 ,2851    ,650.28,638.38,810.24
XS GIS Cut Line= 6
     3027830.941    13820085.349     3029932.958    13819764.794
     3031267.062    13819805.158     3032722.912    13818957.834
      3033729.75    13818241.753     3033816.497    13815550.735
#Sta/Elev= 30
       0   87.42  251.06   86.74  289.87   84.13  487.13   88.33  578.17   84.54
   758.7   86.85 1298.49   82.84 1759.29   85.78 2019.64   82.14 2345.55   84.18
  2842.3   80.45 3324.61   82.82 3358.58   71.47 3377.38   69.85 3393.39   70.53
 3431.51    82.8 3513.64   87.85 3547.44   84.57  3687.2   85.46 3754.61   90.65
  3843.4   82.79 4259.93   80.43    4312   82.83 4797.96   82.97  4940.7   80.32
 5036.87   82.83 5826.09   84.14 6323.08   81.52 6405.33   86.16 9073.48   89.06
#Mann= 3 , 0 , 0
       0     .08       0 3324.61     .04       0 3431.51      .1       0
#XS Ineff= 2 , 0
       0    2910            3567       0
Permanent Ineff=
       T       T
Bank Sta=3324.61,3431.51
XS Rating Curve= 0
Exp/Cntr=.3,.1

Type RM Length L Ch R = 1 ,2213    ,368.45,385.91,702.69
XS GIS Cut Line= 5
     3027884.271    13820415.455     3029876.565    13820611.983
     3031059.706    13820432.628     3031240.638    13820449.258
     3034499.498    13819098.205
#Sta/Elev= 30
       0   85.59  430.31   88.28  535.82   85.52  776.98   87.32 1589.94   82.81
 1771.79   85.72  2375.6   82.26 2968.82   84.71 3244.99   81.66 3284.02   69.63
 3297.62   69.22  3322.7   71.03 3355.32   82.77  3880.3   85.21 3912.77   89.24
 3945.25   83.08 4123.87   81.61 4959.54   83.25 5177.64   80.64 5325.47   83.39
  5418.7   81.09 5935.25   82.17 5974.99   78.24 6007.47   83.61 6056.18   84.36
  6104.9   83.58 6137.37   79.17 6186.09   83.12 6267.28   83.62 6908.13   82.55
#Mann= 3 , 0 , 0
       0     .08       0 3244.99     .04       0 3355.32      .1       0
#XS Ineff= 2 , 0
       0    2960            3417       0
Permanent Ineff=
       T       T
Bank Sta=3244.99,3355.32
XS Rating Curve= 0
Exp/Cntr=.3,.1

Type RM Length L Ch R = 1 ,1827    ,96.86,92.89,165.65
XS GIS Cut Line= 6
     3027889.144    13820445.619     3031155.828    13820829.094
     3031227.353    13820835.334      3031229.68    13820835.564
     3031337.203    13820844.964     3034449.077    13820370.773
#Sta/Elev= 30
       0   85.88  139.31   87.79  440.88   87.86  531.98   85.92 1392.85   86.61
 1570.26   86.13 1649.61   83.15 1770.43   85.86 2374.51   82.24 2978.67   83.75
 3215.27   81.22 3255.88   69.85 3269.61   69.35 3295.64   70.48  3316.7   79.24
 3332.88   81.96 3537.23   81.54 3807.17   85.53 3855.87   89.62 3871.04   84.61
 3885.83   83.13 4022.77    81.1    4189    83.3 4933.16   81.85 5130.41    83.9
 5312.49   81.94 5722.16   82.89 5904.24   80.49 6506.35   82.86 6618.97   80.43
#Mann= 3 , 0 , 0
       0     .08       0 3215.27     .04       0 3332.88      .1       0
#XS Ineff= 2 , 0
       0    3188            3415       0
Permanent Ineff=
       T       T
Bank Sta=3215.27,3332.88
XS Rating Curve= 0
Exp/Cntr=.5,.3

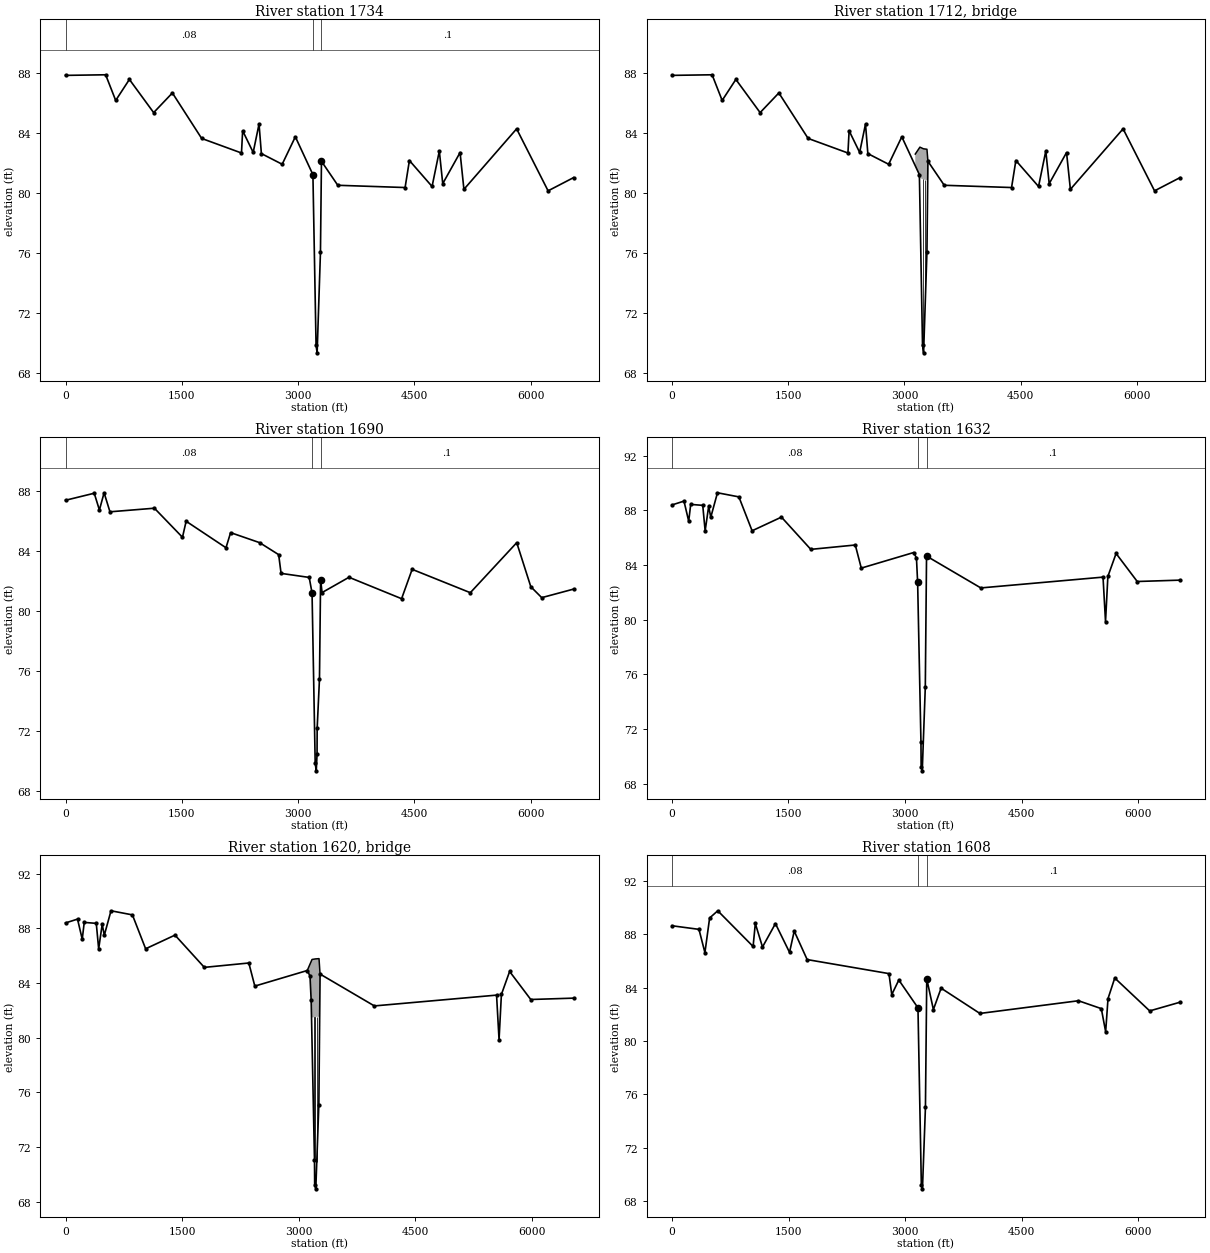
Type RM Length L Ch R = 1 ,1734    ,39.62,43.79,45.26
XS GIS Cut Line= 4
     3027903.367    13820533.654     3031039.482    13820912.463
     3031222.188    13820926.827     3034411.655    13821315.269
#Sta/Elev= 30
       0   87.83  517.87   87.87  647.62   86.16  824.28   87.56 1137.34   85.35
 1379.08   86.66 1756.81   83.63 2270.52   82.66 2285.63   84.14 2421.61    82.7
 2497.15   84.59 2527.37   82.62 2795.72   81.91 2965.53   83.74 3192.27   81.22
 3232.88   69.85 3246.61   69.35 3289.61   76.05  3302.5   82.11 3513.18   80.51
  4381.7   80.36 4437.24   82.16 4729.75   80.43 4823.35   82.79  4867.4   80.62
 5091.08   82.69 5140.68   80.24 5820.67   84.27  6226.7   80.14 6555.21   81.02
#Mann= 3 , 0 , 0
       0     .08       0 3192.27     .04       0  3302.5      .1       0
#XS Ineff= 2 , 0
       0    3167            3414       0
Permanent Ineff=
       T       T
Bank Sta=3192.27,3302.5
XS Rating Curve= 0
Exp/Cntr=.5,.3

Type RM Length L Ch R = 3 ,1712    ,,,
BEGIN DESCRIPTION:
Alief-Clodine Bridge
END DESCRIPTION:
Bridge Culvert--1,0,-1,-1, 0
Deck Dist Width WeirC Skew NumUp NumDn MinLoCord MaxHiCord MaxSubmerge Is_Ogee
1,42,2.6,0, 5, 5, , , .95, 0, 0,0,,
  3139.4 3199.03 3245.03 3290.03 3302.51
   82.59   83.05   82.94   82.91   82.12
       0      81   80.89   80.86       0
 3142.49 3186.03 3232.03 3277.03  3289.5
   82.25   83.05   82.94   82.91   82.13
       0      81   80.89   80.86       0
Pier Skew, UpSta & Num, DnSta & Num=  ,3238.03, 2 ,3225.03, 2 , 0 , 0 , 0 ,,
    1.25    1.25
       0     100
    1.25    1.25
       0     100
Pier Skew, UpSta & Num, DnSta & Num=  ,3268.03, 2 ,3255.03, 2 , 0 , 0 , 0 ,,
    1.25    1.25
       0     100
    1.25    1.25
       0     100
BR Coef=-1 , 1 , 1 ,1.25, 0 ,,,.8,-1,2,0,
WSPro=,,,, 1 ,,,, 0 ,,,, 0 ,,,,-1 ,-1 ,-1 , 0 , 0 , 0 , 0 , 0
BC Design=,, 0 ,, 0 ,,,,,,
BC HTab HWMax=88.16

Type RM Length L Ch R = 1 ,1690    ,59.25,58.75,65.79
XS GIS Cut Line= 6
     3027908.588    13820565.971     3031132.294    13820963.644
     3031204.716    13820969.974      3031207.06    13820970.204
     3031327.811    13820980.754     3034409.096    13821379.847
#Sta/Elev= 30
       0   87.41  370.54   87.88   437.2   86.76  497.66   87.91  573.22   86.64
 1146.36   86.88 1508.41   84.94 1555.61   86.01 2069.48   84.24 2129.06   85.25
 2503.69   84.58 2748.73   83.78 2779.82   82.53 3142.55   82.26 3179.27   81.22
 3219.88   69.85 3233.61   69.35 3243.84   70.47 3245.18   72.18 3275.08   75.49
  3289.5   82.11 3308.58   81.25 3655.85   82.27 4333.98   80.84 4470.08    82.8
 5220.15   81.24 5818.77   84.58 6000.27   81.64 6141.07   80.91 6551.43   81.48
#Mann= 3 , 0 , 0
       0     .08       0 3179.27     .04       0  3289.5      .1       0
#XS Ineff= 2 , 0
       0    3162            3410       0
Permanent Ineff=
       T       T
Bank Sta=3179.27,3289.5
XS Rating Curve= 0
Exp/Cntr=.5,.3

Type RM Length L Ch R = 1 ,1632    ,24.17,24.15,26.24
XS GIS Cut Line= 6
      3027918.72    13820628.684     3031122.159    13821021.577
     3031215.765    13821027.297     3031264.185    13821036.487
     3031300.678    13821038.917     3034408.959    13821429.115
#Sta/Elev= 30
       0   88.39  154.56   88.67  215.38    87.2  241.11   88.43  396.13   88.36
  426.96   86.49  472.29   88.29  499.48   87.49  585.61   89.28  861.21   88.98
 1031.45    86.5 1409.26    87.5 1787.07   85.14 2359.78   85.46  2436.9   83.77
  3111.8   84.91 3147.19   84.51  3162.3   82.72 3205.15   71.03 3207.45   69.24
 3221.84   68.94 3261.08   75.08 3276.98   84.65 3975.64   82.32 5548.85   83.11
 5580.92   79.85 5611.15   83.16 5716.98   84.84  5989.1   82.79 6539.84   82.89
#Mann= 3 , 0 , 0
       0     .08       0  3162.3     .04       0 3276.98      .1       0
#XS Ineff= 2 , 0
       0    3153            3390       0
Permanent Ineff=
       T       T
Bank Sta=3162.3,3276.98
XS Rating Curve= 0
Exp/Cntr=.5,.3

Type RM Length L Ch R = 3 ,1620    ,,,
BEGIN DESCRIPTION:
RR Bridge
END DESCRIPTION:
Bridge Culvert--1,0,-1,-1, 0
Deck Dist Width WeirC Skew NumUp NumDn MinLoCord MaxHiCord MaxSubmerge Is_Ogee
.1,24,2.6,0, 5, 5, , , .95, 0, 0,0,,
 3111.81 3173.42 3218.42 3263.42 3276.96
   84.91   85.72   85.76   85.78   84.62
       0   81.47   81.51   81.53       0
 3119.17 3173.42 3218.42 3263.42 3276.96
   83.67   85.72   85.76   85.78   84.64
       0   81.47   81.51   81.53       0
Pier Skew, UpSta & Num, DnSta & Num=  ,3204.42, 2 ,3204.42, 2 , 0 , 0 , 0 ,,
       2       2
       0     100
       2       2
       0     100
Pier Skew, UpSta & Num, DnSta & Num=  ,3234.42, 2 ,3234.42, 2 , 0 , 0 , 0 ,,
       2       2
       0     100
       2       2
       0     100
BR Coef=-1 , 1 , 1 ,1.25, 0 ,,,.8,-1,2,0,
WSPro=,,,, 1 ,,,, 0 ,,,, 0 ,,,,-1 ,-1 ,-1 , 0 , 0 , 0 , 0 , 0
BC Design=,, 0 ,, 0 ,,,,,,
BC HTab HWMax=89.28

Type RM Length L Ch R = 1 ,1608    ,100.47,89.62,93.77
XS GIS Cut Line= 6
     3027921.986    13820648.904     3031117.402     13821045.34
     3031211.385     13821051.25     3031258.688     13821060.23
     3031296.245     13821062.73     3034406.425    13821453.156
#Sta/Elev= 30
       0   88.62  347.32   88.35  423.74   86.61   484.2    89.2   588.9   89.74
 1043.45   87.07 1072.07   88.79 1164.37   87.03 1330.64   88.78 1512.02   86.63
 1572.42   88.22 1738.74   86.09 2790.74   85.04 2827.02   83.47 2917.71   84.56
 3164.02   82.48 3207.45   69.24 3221.84   68.94 3260.18   75.04 3276.98   84.65
 3362.31   82.35 3461.69   83.95 3960.57   82.06 5228.42   83.01 5522.31   82.42
 5578.17   80.69  5608.4   83.17 5695.19   84.71 6144.67   82.25 6534.54    82.9
#Mann= 3 , 0 , 0
       0     .08       0 3164.02     .04       0 3276.98      .1       0
#XS Ineff= 2 , 0
       0    3151            3374       0
Permanent Ineff=
       T       T
Bank Sta=3164.02,3276.98
XS Rating Curve= 0
Exp/Cntr=.5,.3

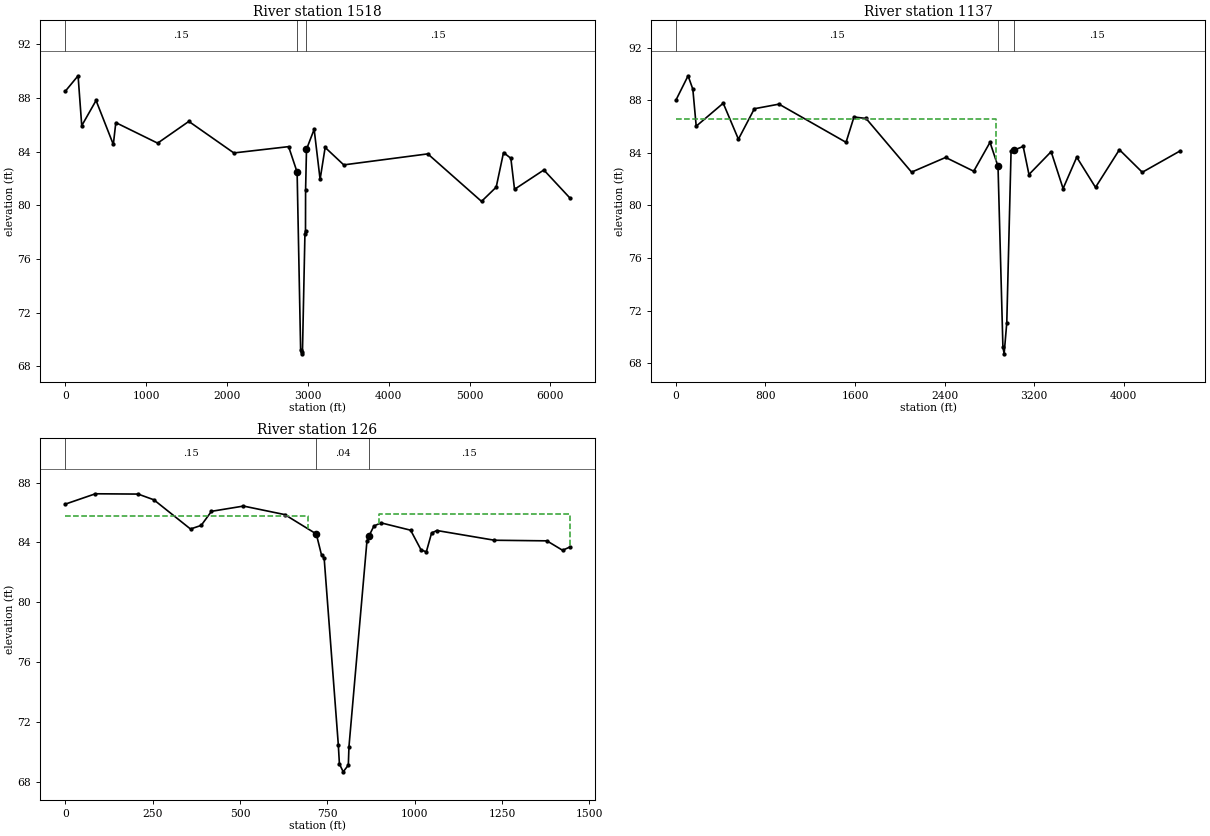
Type RM Length L Ch R = 1 ,1518    ,386.95,380.96,386.91
XS GIS Cut Line= 4
     3028200.139    13820897.394     3031026.801    13821133.657
     3031197.134    13821137.914     3034403.175    13821529.292
#Sta/Elev= 30
       0   88.51  157.91   89.66  203.07   85.94  380.25   87.82  593.78   84.54
  624.53   86.17 1141.82   84.64 1527.67   86.26  2084.6   83.91  2761.9   84.38
 2867.02   82.48 2910.45   69.24 2924.84   68.94 2933.26    69.1  2963.7   77.87
 2970.73   78.09 2971.79   81.13 2983.08   84.18 3077.79   85.67 3151.24   81.94
  3213.8   84.32 3443.85   83.02 4483.15   83.84  5147.9    80.3 5329.38   81.36
 5420.05   83.94 5510.72   83.51 5556.05    81.2 5918.73   82.64 6236.75   80.58
#Mann= 3 , 0 , 0
       0     .15       0 2867.02     .04       0 2983.08     .15       0
#XS Ineff= 2 , 0
       0    2860            3025       0
Permanent Ineff=
       T       T
Bank Sta=2867.02,2983.08
XS Rating Curve= 0
Exp/Cntr=.3,.1

Type RM Length L Ch R = 1 ,1137    ,1008.64,1010.77,1003.86
XS GIS Cut Line= 6
     3028222.649    13820998.692     3029156.838    13821099.989
     3029796.641    13821336.401     3031182.411    13821512.279
     3032282.766    13821712.998     3032555.936    13821955.391
#Sta/Elev= 30
       0   88.03  108.35   89.88  150.73   88.86  180.91   86.04  422.31   87.79
   558.1   85.05  700.66   87.37  920.66   87.72 1519.89   84.81 1590.68   86.74
 1698.49   86.63 2105.23   82.54 2409.82   83.66 2660.66   82.61 2806.25   84.81
  2877.8   82.98 2921.52   69.23 2932.42    68.7 2956.08   71.07 2994.45   84.16
 3016.67    84.2 3102.65    84.5 3154.24   82.36 3352.46    84.1 3459.19   81.29
 3581.17   83.68 3748.89   81.38 3962.36   84.25  4166.9   82.53 4505.72   84.16
#Mann= 3 , 0 , 0
       0     .15       0  2877.8     .04       0 3016.67     .15       0
#XS Ineff= 2 , 0
       0 2861.01   86.57    3024       0
Permanent Ineff=
       T       T
Bank Sta=2877.8,3016.67
XS Rating Curve= 0
Exp/Cntr=.3,.1

Type RM Length L Ch R = 1 ,126     ,54.53,126.49,5.26
BEGIN DESCRIPTION:
126.488
END DESCRIPTION:
XS GIS Cut Line= 2
      3030264.18    13822519.536     3031707.407    13822532.591
#Sta/Elev= 30
       0   86.56   86.14   87.25  208.33   87.23  253.33   86.85  358.33    84.9
  388.89   85.14  418.34   86.08  509.99   86.43  628.35   85.86  718.35   84.57
  733.35   83.16   740.8   82.98  781.36   70.52  784.52   69.23  795.42    68.7
  810.07   69.15  811.88   70.38  863.37    84.1  868.36    84.4  883.36    85.1
  903.57   85.31  988.36   84.82 1018.36    83.5 1033.36   83.38 1048.36   84.63
 1063.36    84.8 1228.37   84.15 1378.38   84.11 1423.38   83.48 1443.29   83.69
#Mann= 3 , 0 , 0
       0     .15       0  718.35     .04       0  868.36     .15       0
#XS Ineff= 2 , 0
       0  693.52   85.77  897.38       0   85.91
Permanent Ineff=
       T       T
Bank Sta=718.35,868.36
XS Rating Curve= 0
Exp/Cntr=.3,.1

Chan Stop Cuts=-1

--- D132-00-00_Updated.g03 (geometry) ---

Geom Title=D132-00-00 June 2007
Version=Version 3.0.1  Mar 2001

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
River Reach=D132-00-00      ,D132-00-00_0001