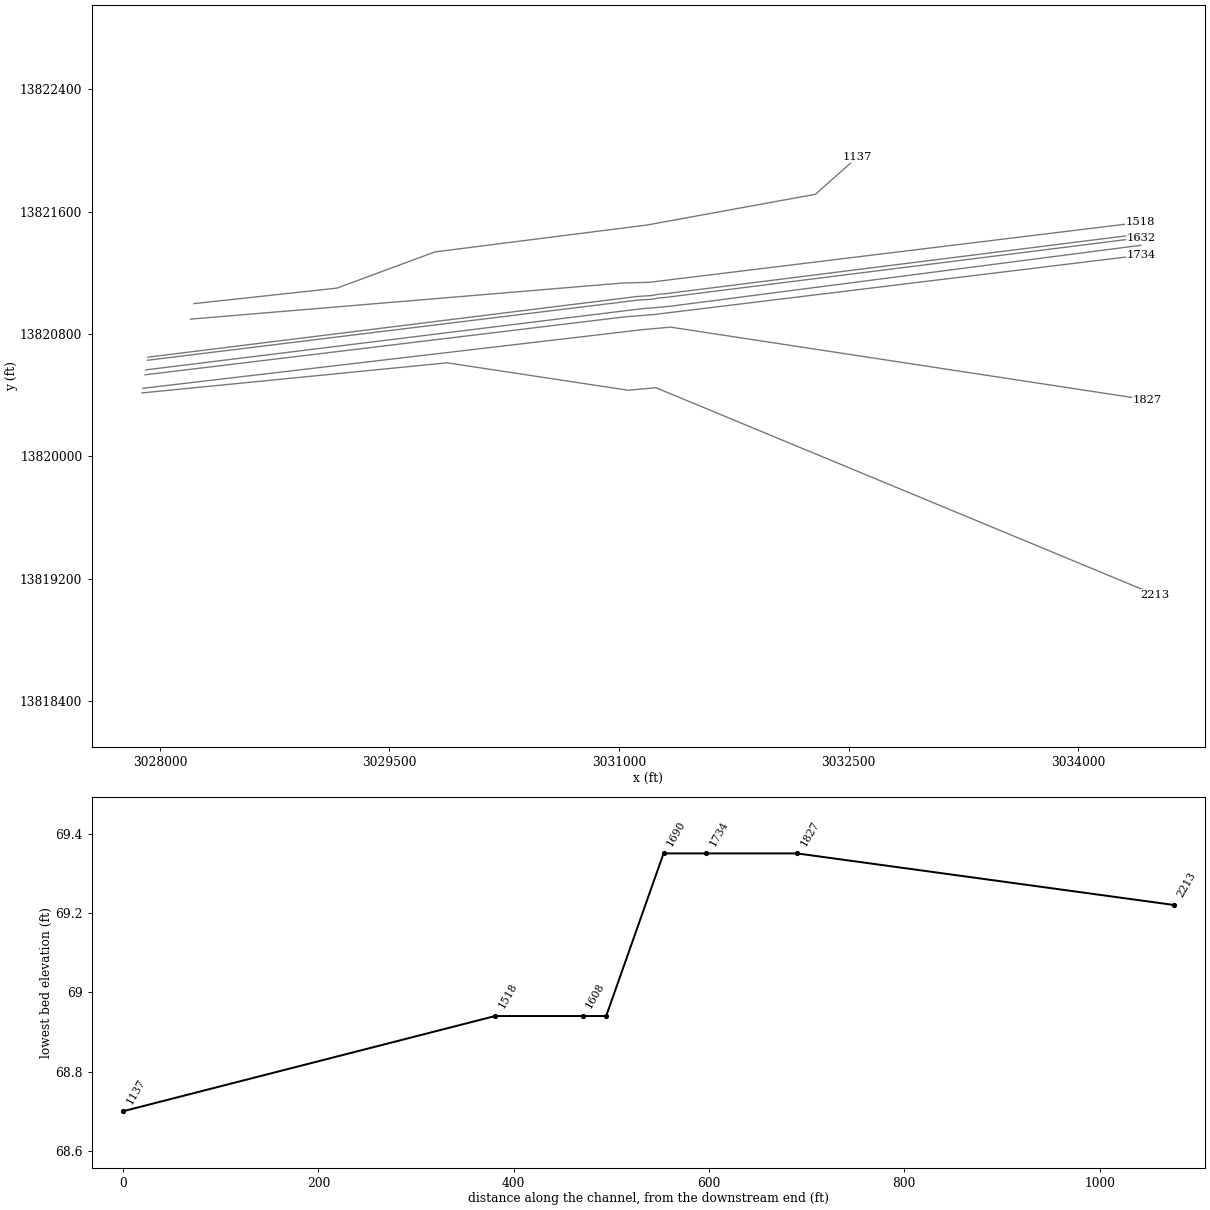
HEC-RAS study D132-00-00_Updated.prj: D132-00-00

--- D132-00-00_Updated.g03 (geometry) --- (continued)

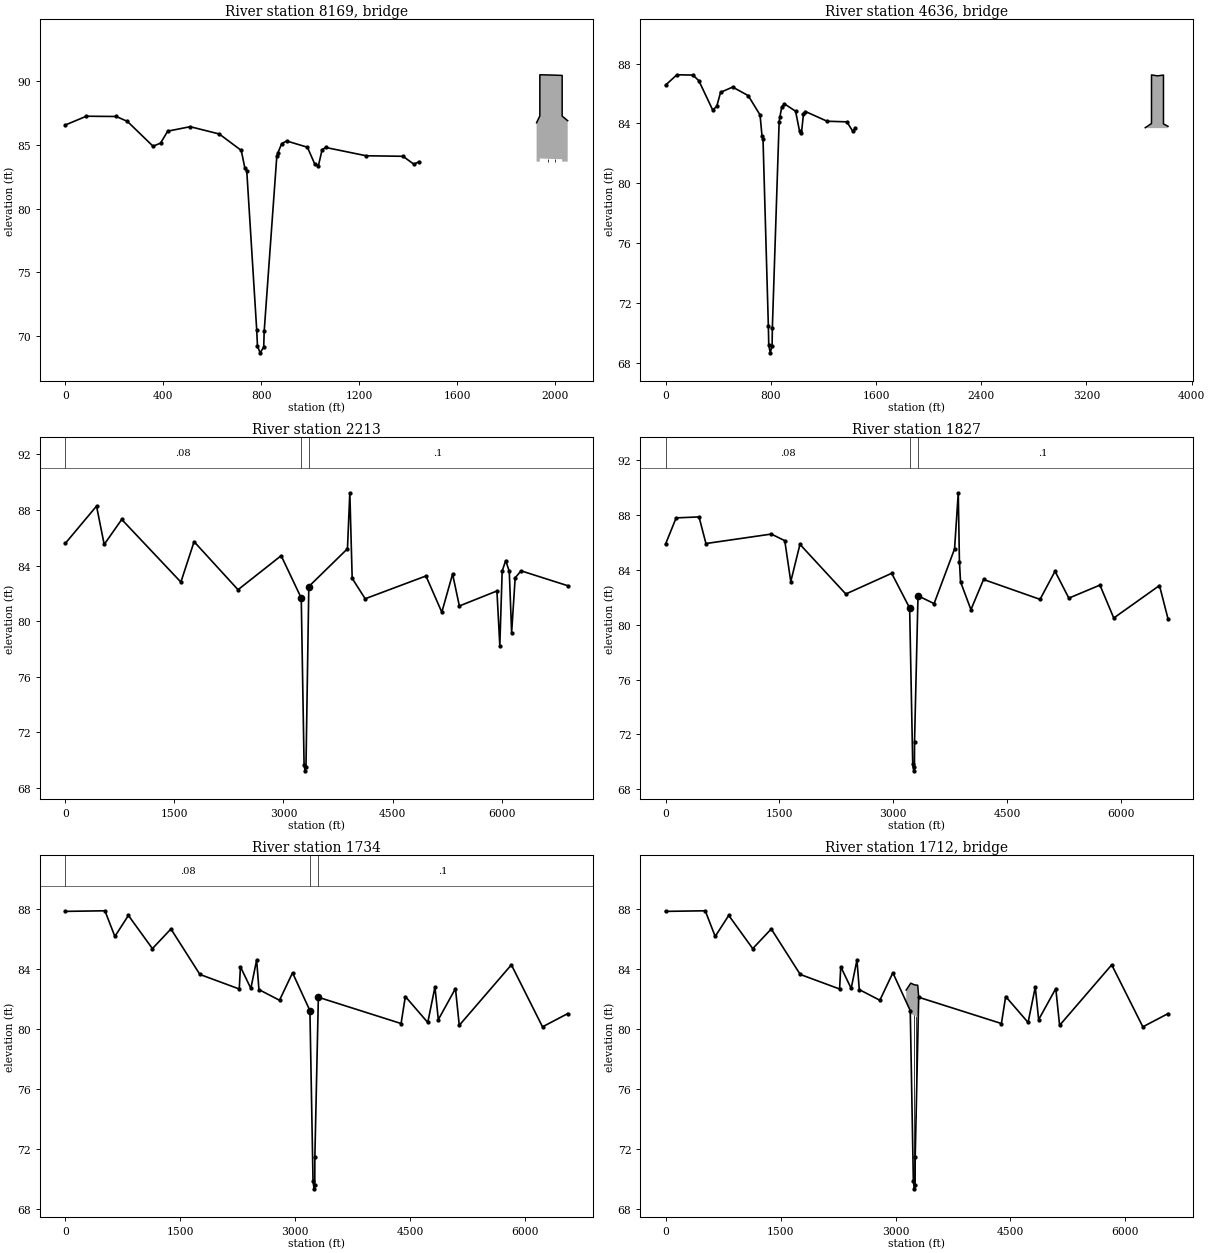
Type RM Length L Ch R = 3 ,8169    ,,,
BEGIN DESCRIPTION:
Addicks-Clodine Bridge
END DESCRIPTION:
Bridge Culvert--1,0,-1,-1, 0
Deck Dist Width WeirC Skew NumUp NumDn MinLoCord MaxHiCord MaxSubmerge Is_Ogee
5,80,2.6,0, 7, 7, , , .95, 0, 0,0,,
 1923.58 1936.87 1936.87 1983.87 2027.97 2027.97 2050.54
   86.74   87.28    90.5   90.48   90.45   87.26    86.9
       0       0   83.94    83.9   83.88       0       0
  1454.5 1482.87 1482.87 1529.87 1573.97 1573.97 1605.12
   86.23   87.28    90.5   90.48   90.45   87.26   86.54
       0       0   83.94    83.9   83.88       0       0
Pier Skew, UpSta & Num, DnSta & Num=  ,1968.87, 2 ,1514.87, 2 , 0 , 0 , 0 ,,
    1.25    1.25
       0     100
    1.25    1.25
       0     100
Pier Skew, UpSta & Num, DnSta & Num=  ,1998.87, 2 ,1544.87, 2 , 0 , 0 , 0 ,,
    1.25    1.25
       0     100
    1.25    1.25
       0     100
BR Coef=-1 , 1 , 1 ,1.25, 0 ,,,.8,-1,2,0,
WSPro=,,,, 1 ,,,, 0 ,,,, 0 ,,,,-1 ,-1 ,-1 , 0 , 0 , 0 , 0 , 0
BC Design=,, 0 ,, 0 ,,,,,,

Type RM Length L Ch R = 3 ,4636    ,,,
BEGIN DESCRIPTION:
Winkleman Bridge
END DESCRIPTION:
Bridge Culvert--1,0,-1,-1, 0
Deck Dist Width WeirC Skew NumUp NumDn MinLoCord MaxHiCord MaxSubmerge Is_Ogee
5,48,2.6,0, 7, 7, , , .95, 0, 0,0,,
 3646.68 3694.21 3694.21 3740.21 3785.21 3785.21 3819.79
   83.72      84   87.24   87.18   87.23   83.97   83.81
   81.24   81.24   81.24   81.18   81.23       0       0
 3694.58 3743.21 3743.21 3789.21 3834.21 3834.21 3868.53
   83.73      84   87.24   87.18   87.23   83.97      84
   81.24   81.24   81.24   81.18   81.23       0       0
Pier Skew, UpSta & Num, DnSta & Num=  ,3726.21, 2 ,3775.21, 2 , 0 , 0 , 0 ,,
    1.25    1.25
       0     100
    1.25    1.25
       0     100
Pier Skew, UpSta & Num, DnSta & Num=  ,3750.21, 2 ,3799.21, 2 , 0 , 0 , 0 ,,
    1.25    1.25
       0     100
    1.25    1.25
       0     100
BR Coef=-1 , 1 , 1 ,1.25, 0 ,,,.8,-1,2,0,
WSPro=,,,, 1 ,,,, 0 ,,,, 0 ,,,,-1 ,-1 ,-1 , 0 , 0 , 0 , 0 , 0
BC Design=,, 0 ,, 0 ,,,,,,

Type RM Length L Ch R = 1 ,2213    ,368.45,385.91,702.69
XS GIS Cut Line= 5
     3027884.271    13820415.455     3029876.565    13820611.983
     3031059.706    13820432.628     3031240.638    13820449.258
     3034499.498    13819098.205
#Sta/Elev= 30
       0   85.59  430.31   88.28  535.82   85.52  776.98   87.32 1589.94   82.81
 1771.79   85.72  2375.6   82.26 2968.82   84.71 3244.99   81.66 3284.02   69.63
 3297.62   69.22 3309.87    69.5 3348.99   82.49  3880.3   85.21 3912.77   89.24
 3945.25   83.08 4123.87   81.61 4959.54   83.25 5177.64   80.64 5325.47   83.39
  5418.7   81.09 5935.25   82.17 5974.99   78.24 6007.47   83.61 6056.18   84.36
  6104.9   83.58 6137.37   79.17 6186.09   83.12 6267.28   83.62 6908.13   82.55
#Mann= 3 , 0 , 0
       0     .08       0 3244.99     .04       0 3348.99      .1       0
#XS Ineff= 2 , 0
       0    2960            3417       0
Permanent Ineff=
       T       T
Bank Sta=3244.99,3348.99
XS Rating Curve= 0
Exp/Cntr=.3,.1

Type RM Length L Ch R = 1 ,1827    ,96.86,92.89,165.65
XS GIS Cut Line= 6
     3027889.144    13820445.619     3031155.828    13820829.094
     3031227.353    13820835.334      3031229.68    13820835.564
     3031337.203    13820844.964     3034449.077    13820370.773
#Sta/Elev= 30
       0   85.88  139.31   87.79  440.88   87.86  531.98   85.92 1392.85   86.61
 1570.26   86.13 1649.61   83.15 1770.43   85.86 2374.51   82.24 2978.67   83.75
 3215.27   81.22 3255.88   69.85 3269.61   69.35 3278.63   69.61 3279.69   71.44
  3325.5   82.11 3537.23   81.54 3807.17   85.53 3855.87   89.62 3871.04   84.61
 3885.83   83.13 4022.77    81.1    4189    83.3 4933.16   81.85 5130.41    83.9
 5312.49   81.94 5722.16   82.89 5904.24   80.49 6506.35   82.86 6618.97   80.43
#Mann= 3 , 0 , 0
       0     .08       0 3215.27     .04       0  3325.5      .1       0
#XS Ineff= 2 , 0
       0    3188            3415       0
Permanent Ineff=
       T       T
Bank Sta=3215.27,3325.5
XS Rating Curve= 0
Exp/Cntr=.5,.3

Type RM Length L Ch R = 1 ,1734    ,39.62,43.79,45.26
XS GIS Cut Line= 4
     3027903.367    13820533.654     3031039.482    13820912.463
     3031222.188    13820926.827     3034411.655    13821315.269
#Sta/Elev= 30
       0   87.83  517.87   87.87  647.62   86.16  824.28   87.56 1137.34   85.35
 1379.08   86.66 1756.81   83.63 2270.52   82.66 2285.63   84.14 2421.61    82.7
 2497.15   84.59 2527.37   82.62 2795.72   81.91 2965.53   83.74 3192.27   81.22
 3232.88   69.85 3246.61   69.35 3255.63   69.61 3256.69   71.44  3302.5   82.11
  4381.7   80.36 4437.24   82.16 4729.75   80.43 4823.35   82.79  4867.4   80.62
 5091.08   82.69 5140.68   80.24 5820.67   84.27  6226.7   80.14 6555.21   81.02
#Mann= 3 , 0 , 0
       0     .08       0 3192.27     .04       0  3302.5      .1       0
#XS Ineff= 2 , 0
       0    3167            3414       0
Permanent Ineff=
       T       T
Bank Sta=3192.27,3302.5
XS Rating Curve= 0
Exp/Cntr=.5,.3

Type RM Length L Ch R = 3 ,1712    ,,,
BEGIN DESCRIPTION:
Alief-Clodine Bridge
END DESCRIPTION:
Bridge Culvert--1,0,-1,-1, 0
Deck Dist Width WeirC Skew NumUp NumDn MinLoCord MaxHiCord MaxSubmerge Is_Ogee
1,42,2.6,0, 5, 5, , , .95, 0, 0,0,,
  3139.4 3199.03 3245.03 3290.03 3302.51
   82.59   83.05   82.94   82.91   82.12
       0      81   80.89   80.86       0
 3142.49 3186.03 3232.03 3277.03  3289.5
   82.25   83.05   82.94   82.91   82.13
       0      81   80.89   80.86       0
Pier Skew, UpSta & Num, DnSta & Num=  ,3238.03, 2 ,3225.03, 2 , 0 , 0 , 0 ,,
    1.25    1.25
       0     100
    1.25    1.25
       0     100
Pier Skew, UpSta & Num, DnSta & Num=  ,3268.03, 2 ,3255.03, 2 , 0 , 0 , 0 ,,
    1.25    1.25
       0     100
    1.25    1.25
       0     100
BR Coef=-1 , 1 , 1 ,1.25, 0 ,,,.8,-1,2,0,
WSPro=,,,, 1 ,,,, 0 ,,,, 0 ,,,,-1 ,-1 ,-1 , 0 , 0 , 0 , 0 , 0
BC Design=,, 0 ,, 0 ,,,,,,

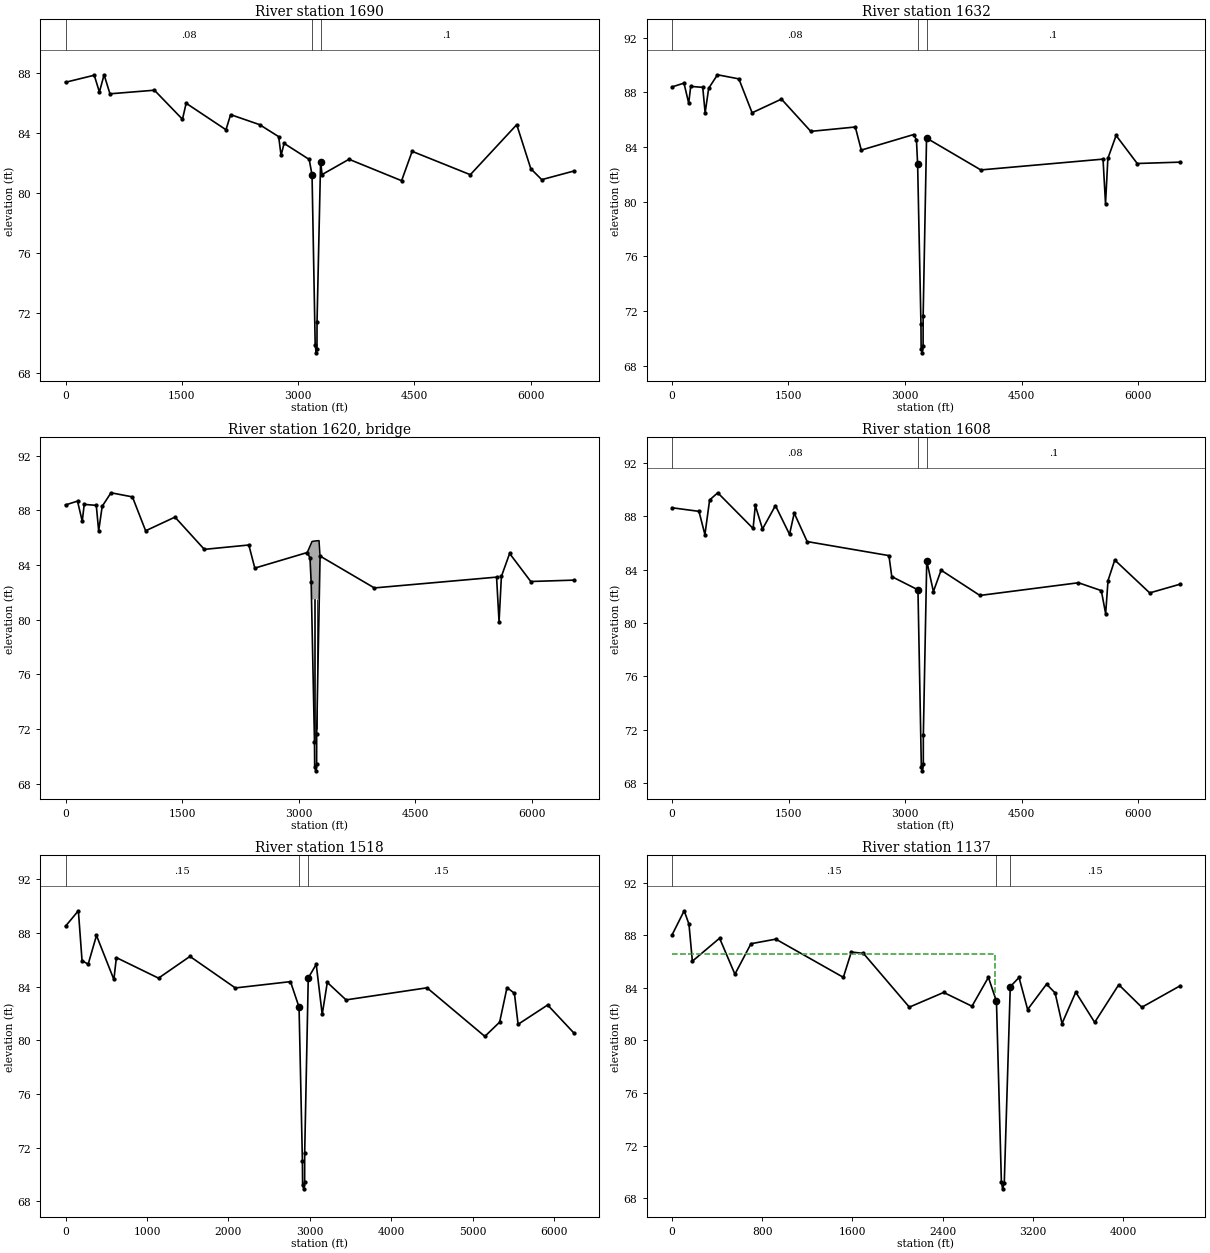
Type RM Length L Ch R = 1 ,1690    ,59.25,58.75,65.79
XS GIS Cut Line= 6
     3027908.588    13820565.971     3031132.294    13820963.644
     3031204.716    13820969.974      3031207.06    13820970.204
     3031327.811    13820980.754     3034409.096    13821379.847
#Sta/Elev= 30
       0   87.41  370.54   87.88   437.2   86.76  497.66   87.91  573.22   86.64
 1146.36   86.88 1508.41   84.94 1555.61   86.01 2069.48   84.24 2129.06   85.25
 2503.69   84.58 2748.73   83.78 2779.82   82.53 2818.68   83.33 3142.55   82.26
 3179.27   81.22 3219.88   69.85 3233.61   69.35 3242.63   69.61 3243.69   71.44
  3289.5   82.11 3308.58   81.25 3655.85   82.27 4333.98   80.84 4470.08    82.8
 5220.15   81.24 5818.77   84.58 6000.27   81.64 6141.07   80.91 6551.43   81.48
#Mann= 3 , 0 , 0
       0     .08       0 3179.27     .04       0  3289.5      .1       0
#XS Ineff= 2 , 0
       0    3162            3410       0
Permanent Ineff=
       T       T
Bank Sta=3179.27,3289.5
XS Rating Curve= 0
Exp/Cntr=.5,.3

Type RM Length L Ch R = 1 ,1632    ,24.17,24.15,26.24
XS GIS Cut Line= 6
      3027918.72    13820628.684     3031122.159    13821021.577
     3031215.765    13821027.297     3031264.185    13821036.487
     3031300.678    13821038.917     3034408.959    13821429.115
#Sta/Elev= 30
       0   88.39  154.56   88.67  215.38    87.2  241.11   88.43  396.13   88.36
  426.96   86.49  472.29   88.29  585.61   89.28  861.21   88.98 1031.45    86.5
 1409.26    87.5 1787.07   85.14 2359.78   85.46  2436.9   83.77  3111.8   84.91
 3147.19   84.51  3162.3   82.72 3205.15   71.03 3207.45   69.24 3221.84   68.94
 3232.63   69.46 3233.13    71.6 3276.98   84.65 3975.64   82.32 5548.85   83.11
 5580.92   79.85 5611.15   83.16 5716.98   84.84  5989.1   82.79 6539.84   82.89
#Mann= 3 , 0 , 0
       0     .08       0  3162.3     .04       0 3276.98      .1       0
#XS Ineff= 2 , 0
       0    3153            3390       0
Permanent Ineff=
       T       T
Bank Sta=3162.3,3276.98
XS Rating Curve= 0
Exp/Cntr=.5,.3

Type RM Length L Ch R = 3 ,1620    ,,,
BEGIN DESCRIPTION:
RR Bridge
END DESCRIPTION:
Bridge Culvert--1,0,-1,-1, 0
Deck Dist Width WeirC Skew NumUp NumDn MinLoCord MaxHiCord MaxSubmerge Is_Ogee
.1,24,2.6,0, 5, 5, , , .95, 0, 0,0,,
 3111.81 3173.42 3218.42 3263.42 3276.96
   84.91   85.72   85.76   85.78   84.62
       0   81.47   81.51   81.53       0
 3119.17 3173.42 3218.42 3263.42 3276.96
   83.67   85.72   85.76   85.78   84.64
       0   81.47   81.51   81.53       0
Pier Skew, UpSta & Num, DnSta & Num=  ,3204.42, 2 ,3204.42, 2 , 0 , 0 , 0 ,,
       2       2
       0     100
       2       2
       0     100
Pier Skew, UpSta & Num, DnSta & Num=  ,3234.42, 2 ,3234.42, 2 , 0 , 0 , 0 ,,
       2       2
       0     100
       2       2
       0     100
BR Coef=-1 , 1 , 1 ,1.25, 0 ,,,.8,-1,2,0,
WSPro=,,,, 1 ,,,, 0 ,,,, 0 ,,,,-1 ,-1 ,-1 , 0 , 0 , 0 , 0 , 0
BC Design=,, 0 ,, 0 ,,,,,,

Type RM Length L Ch R = 1 ,1608    ,100.47,89.62,93.77
XS GIS Cut Line= 6
     3027921.986    13820648.904     3031117.402     13821045.34
     3031211.385     13821051.25     3031258.688     13821060.23
     3031296.245     13821062.73     3034406.425    13821453.156
#Sta/Elev= 30
       0   88.62  347.32   88.35  423.74   86.61   484.2    89.2   588.9   89.74
 1043.45   87.07 1072.07   88.79 1164.37   87.03 1330.64   88.78 1512.02   86.63
 1572.42   88.22 1738.74   86.09 2790.74   85.04 2827.02   83.47 3164.02   82.48
 3207.45   69.24 3221.84   68.94 3232.63   69.46 3233.13    71.6 3276.98   84.65
 3362.31   82.35 3461.69   83.95 3960.57   82.06 5228.42   83.01 5522.31   82.42
 5578.17   80.69  5608.4   83.17 5695.19   84.71 6144.67   82.25 6534.54    82.9
#Mann= 3 , 0 , 0
       0     .08       0 3164.02     .04       0 3276.98      .1       0
#XS Ineff= 2 , 0
       0    3151            3374       0
Permanent Ineff=
       T       T
Bank Sta=3164.02,3276.98
XS Rating Curve= 0
Exp/Cntr=.5,.3

Type RM Length L Ch R = 1 ,1518    ,386.95,380.96,386.91
XS GIS Cut Line= 4
     3028200.139    13820897.394     3031026.801    13821133.657
     3031197.134    13821137.914     3034403.175    13821529.292
#Sta/Elev= 30
       0   88.51  157.91   89.66  203.07   85.94  278.33   85.68  380.25   87.82
  593.78   84.54  624.53   86.17 1141.82   84.64 1527.67   86.26  2084.6   83.91
  2761.9   84.38 2867.02   82.48 2908.15   71.03 2910.45   69.24 2924.84   68.94
 2935.63   69.46 2936.13    71.6 2979.98   84.65 3077.79   85.67 3151.24   81.94
  3213.8   84.32 3443.85   83.02 4437.81   83.92  5147.9    80.3 5329.38   81.36
 5420.05   83.94 5510.72   83.51 5556.05    81.2 5918.73   82.64 6236.75   80.58
#Mann= 3 , 0 , 0
       0     .15       0 2867.02     .04       0 2979.98     .15       0
#XS Ineff= 2 , 0
       0    2860            3025       0
Permanent Ineff=
       T       T
Bank Sta=2867.02,2979.98
XS Rating Curve= 0
Exp/Cntr=.3,.1

Type RM Length L Ch R = 1 ,1137    ,1008.64,1010.77,1003.86
XS GIS Cut Line= 6
     3028222.649    13820998.692     3029156.838    13821099.989
     3029796.641    13821336.401     3031182.411    13821512.279
     3032282.766    13821712.998     3032555.936    13821955.391
#Sta/Elev= 30
       0   88.03  108.35   89.88  150.73   88.86  180.91   86.04  422.31   87.79
   558.1   85.05  700.66   87.37  920.66   87.72 1519.89   84.81 1590.68   86.74
 1698.49   86.63 2105.23   82.54 2409.82   83.66 2660.66   82.61 2806.25   84.81
  2877.8   82.98 2921.52   69.23 2932.42    68.7 2947.07   69.15 3000.37    84.1
    3078    84.8 3154.24   82.36 3321.96   84.29  3398.2   83.62 3459.19   81.29
 3581.17   83.68 3748.89   81.38 3962.36   84.25  4166.9   82.53 4505.72   84.16
#Mann= 3 , 0 , 0
       0     .15       0  2877.8     .04       0 3000.37     .15       0
#XS Ineff= 2 , 0
       0 2861.01   86.57    3024       0
Permanent Ineff=
       T       T
Bank Sta=2877.8,3000.37
XS Rating Curve= 0
Exp/Cntr=.3,.1